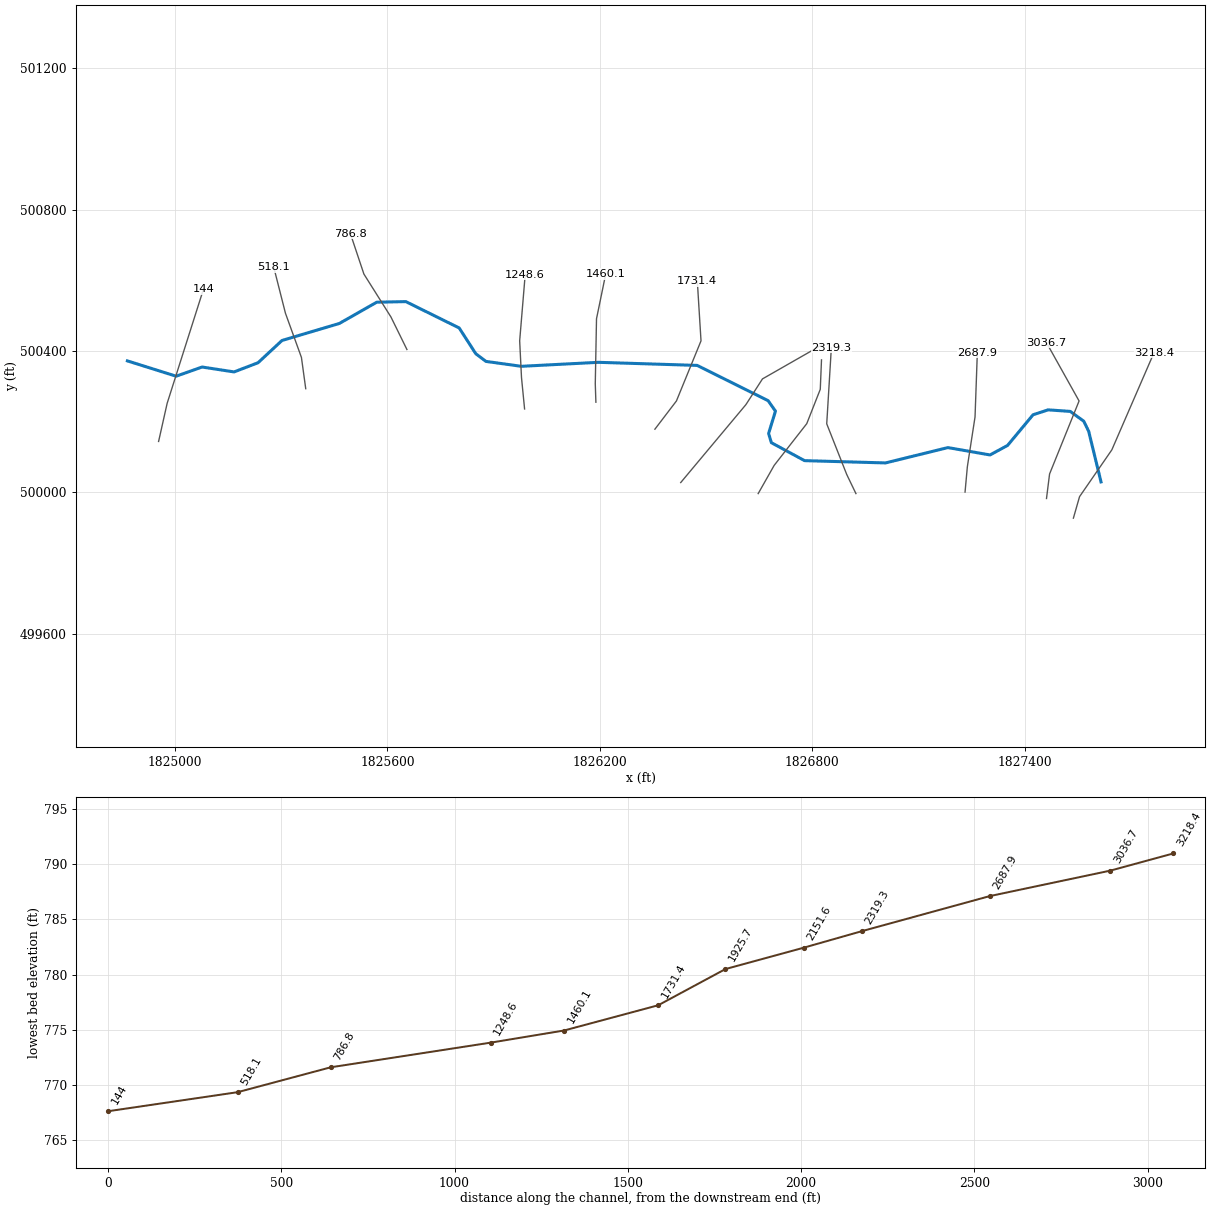
--- MILLCK.prj (project) ---

Proj Title=MILLCK
Current Plan=p01
Default Exp/Contr=0,0
English Units
Geom File=g01
Flow File=f01
Plan File=p01
BEGIN DESCRIPTION:
END DESCRIPTION:
DSS Export Rating Curves= 0
DSS Export Rating Curve Sorted= 0
DSS Export Volume Flow Curves= 0
DXF OffsetX= 0
DXF OffsetY= 0
DXF ScaleX= 0
DXF ScaleY= 0

--- MILLCK.p01 (plan) ---

Plan Title=Floodplain
Program Version=4.00
Geom File=g01
Flow File=f01
K Sum by GR=0
Std Step Tol=0.01
Critical Tol=0.01
Num of Std Step Trials=20
Max Error Tol=0.3
Flow Tol Ratio=0.001
Split Flow NTrial=30
Split Flow Tol=0.02
Split Flow Ratio=0.02
Log Output Level=0
Friction Slope Method=1
Unsteady Friction Slope Method=2
Unsteady Bridges Friction Slope Method=1
Global Log Level=0
CheckData=False
Run HTab=0
Run UNet=0
Run PostProcess=0
UNET Theta=0
UNET Theta Warmup=0
UNET ZTol=0
UNET ZSATol=0
UNET MxIter=0
UNET MaxInSteps=0
UNET DtIC=0
UNET DtMin=0
UNET MaxCRTS=0
UNET WFStab=0
UNET SFStab=0
UNET WFX=0
UNET SFX=0
UNET DSS MLevel=0
UNET DZMax Abort=0
UNET Convert EG Bridges=0
UNET Use Existing IB Tables=0
UNET Froude Limit=0
UNET Froude Power=0
Write IC File=0
Echo Input=False
Echo Output=False
Write Detailed=0

--- MILLCK.f01 (steady flow) ---

Flow Title=NFF Regression Equation
Program Version=4.00
Number of Profiles=1
Profile Names=P100yr
River Rch & RM=MILLCK,Main      ,3218.4
776.8110
River Rch & RM=MILLCK,Main      ,2687.9
1059.804
River Rch & RM=MILLCK,Main      ,1731.4
1108.300
River Rch & RM=MILLCK,Main      ,786.8
1171.867
Boundary for River Rch & Prof#=MILLCK,Main      ,1
Up Type=0
Dn Type=3
Dn Slope=0.005949

--- MILLCK.g01 (geometry) ---

Geom Title=USGS 10m DEM
Program Version=4.10

River Reach=MILLCK          ,Main
Reach XY= 30
     1827615.263      500029.182     1827580.443      500172.224
     1827566.554       500200.87      1827528.36      500228.648
      1827465.86      500232.988     1827423.325      500219.099
     1827351.276      500132.294     1827301.797      500105.384
     1827182.874      500126.217     1827006.658      500082.815
     1826778.058      500089.274     1826684.308      500140.056
     1826676.496      500166.097     1826695.895      500229.516
     1826675.061       500259.03     1826474.672      500358.806
     1826195.895      500367.537     1825978.013      500356.252
     1825878.186      500370.141      1825849.54      500391.842
     1825802.665      500464.759     1825652.063      500539.332
     1825569.914      500537.715     1825464.222      500477.518
     1825302.301      500429.354     1825234.636      500366.391
     1825166.928      500340.349      1825076.65      500354.239
     1825003.403      500328.257     1824865.589      500371.608

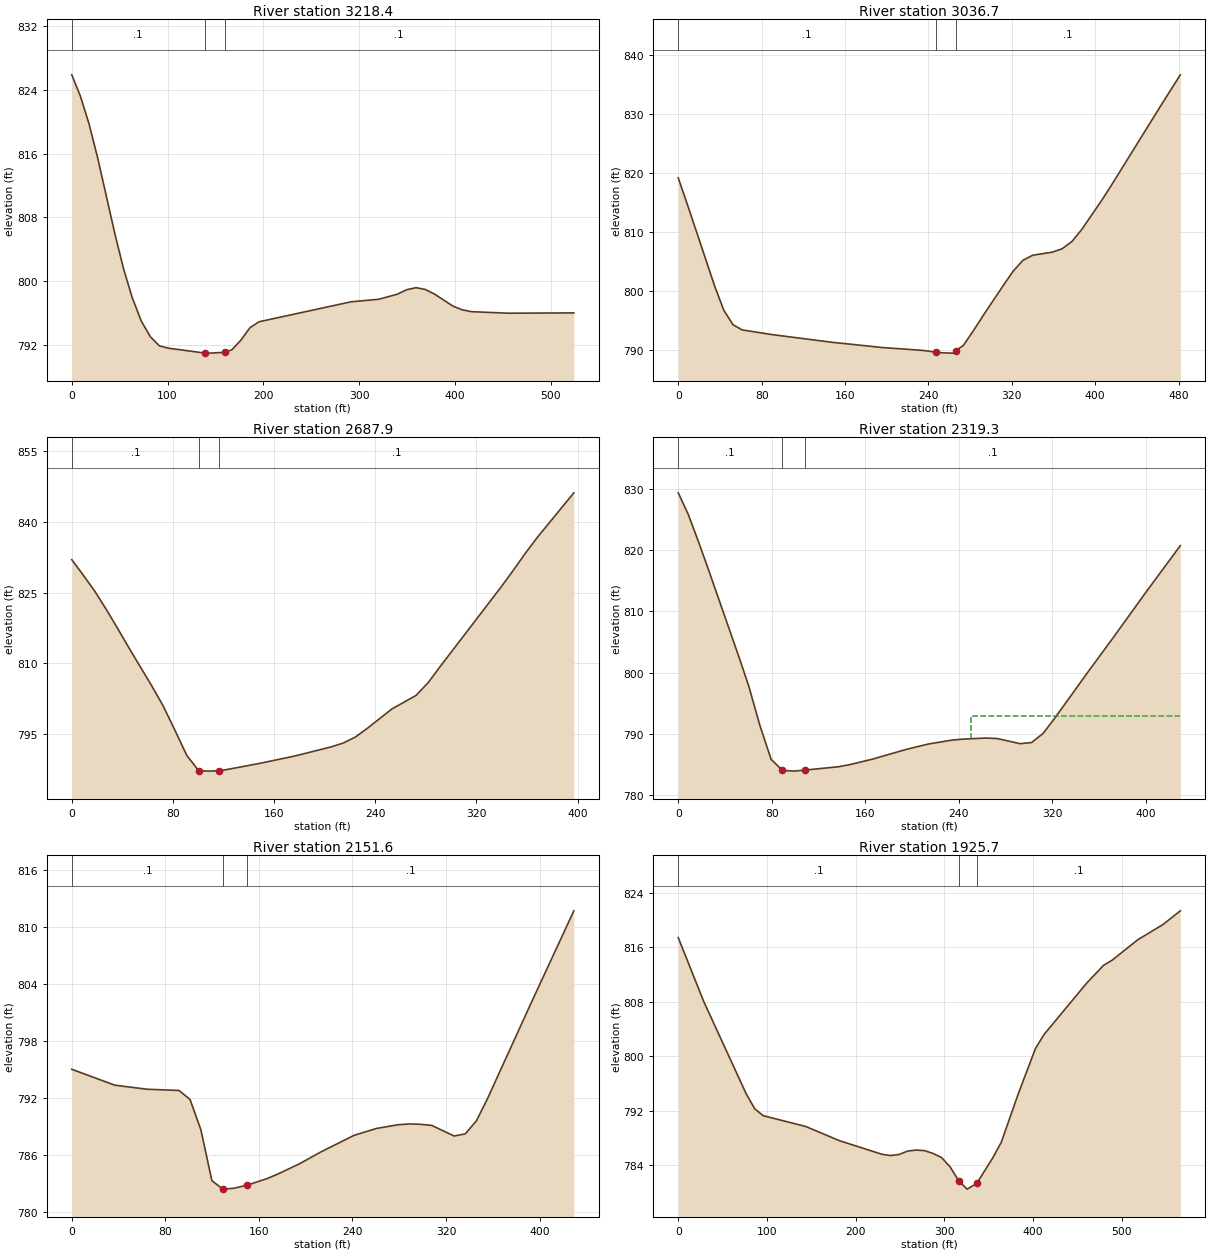
Type RM Length L Ch R = 1 ,3218.4  ,179.5,181.7,182.7
XS GIS Cut Line= 4
     1827537.257      499926.565     1827554.618      499987.329
     1827645.764      500119.707     1827765.122      500395.315
#Sta/Elev= 30
       0  825.86       9  823.19    18.1  819.69    27.1  815.43    45.1   805.9
    54.2  801.51    63.2  797.93    72.6  795.02    82.1  793.05    91.6   791.9
     101  791.62   138.8  791.01   144.6     791   159.6   791.1   167.2  791.42
   176.6  792.62   186.1  794.19   195.6  794.93   291.7  797.43   320.8  797.75
   340.2  798.39   349.9  798.95   359.6   799.2   369.2  798.97   378.9  798.39
   398.3  796.87     408  796.42   417.7  796.19   456.4     796   524.3  796.04
#Mann= 3 , 0 , 0
       0      .1       0   138.8    .045       0   159.6      .1       0
Bank Sta=138.8,159.6
XS Rating Curve= 0 ,0
Exp/Cntr=0.3,0.1

Type RM Length L Ch R = 1 ,3036.7  ,343.5,348.8,354
XS GIS Cut Line= 4
     1827461.303       499982.12     1827469.983      500051.565
     1827553.316      500258.162     1827461.303      500423.092
#Sta/Elev= 29
       0  819.19     8.8  814.65      35  800.79    43.7  796.72    52.5  794.27
    61.2  793.39    89.4   792.6   147.5  791.28   195.9  790.39   234.6   789.9
   247.2  789.61     254  789.48   263.7  789.44  266.16  789.87   273.4  790.72
   283.1  793.24   292.8   795.9   311.6  800.87   321.1   803.3   330.5  805.18
     340  806.05   358.9  806.58   368.3  807.16   377.7  808.39   387.2  810.46
   406.1  815.34   415.5  817.93   462.7  831.38   481.6  836.67
#Mann= 3 , 0 , 0
       0      .1       0   247.2    .045       0  266.16      .1       0
Bank Sta=247.2,266.16
XS Rating Curve= 0 ,0
Exp/Cntr=0.3,0.1

Type RM Length L Ch R = 1 ,2687.9  ,355.9,368.6,381.3
XS GIS Cut Line= 4
     1827231.268      500000.349     1827237.778      500071.964
      1827259.48      500213.023      1827265.99      500395.315
#Sta/Elev= 29
       0  831.96       9  828.72      18  825.35      27  821.55      36  817.51
    44.9   813.4    62.9  805.35    71.9  801.14    81.4  795.89    90.9  790.48
   100.4   787.2     110  787.12   116.8  787.25   119.5   787.3     148  788.73
   176.6  790.34   205.1  792.26   214.6  793.07   224.2  794.34   233.8  796.21
     253  800.28   272.2  803.17   281.8  805.88   291.4  809.34   339.4  826.14
     349  829.66   358.6   833.3   368.2  836.72     397  846.14
#Mann= 3 , 0 , 0
       0      .1       0   100.4    .045       0   116.8      .1       0
Bank Sta=100.4,116.8
XS Rating Curve= 0 ,0
Exp/Cntr=0.3,0.1

Type RM Length L Ch R = 1 ,2319.3  ,191.6,167.7,143.4
XS GIS Cut Line= 4
     1826923.108      499996.009     1826897.066      500050.263
     1826840.643      500193.492     1826853.664      500408.336
#Sta/Elev= 30
       0  829.36     8.6  825.83    17.2  821.44    25.8  816.86    51.6  802.75
    60.2   797.9    69.8  791.42    79.4  785.88    88.5  784.17      89  784.08
    98.7  783.94   108.3  784.11   137.2  784.66   146.8     785     166  785.89
   194.9  787.48   204.5  787.93   214.1  788.37   233.7  788.99   243.5  789.16
     263  789.34   272.8  789.26   292.4  788.42   302.2  788.61     312  790.08
   321.7   792.5   351.1   800.3   370.7  805.38     400  813.14   429.4  820.74
#Mann= 3 , 0 , 0
       0      .1       0    88.5    .045       0   108.3      .1       0
#XS Ineff= 2 , 0
                          250.66          792.88
Permanent Ineff=
       F       F
Bank Sta=88.5,108.3
XS Rating Curve= 0 ,0
Exp/Cntr=0.3,0.1

Type RM Length L Ch R = 1 ,2151.6  ,223.9,225.9,227.7
XS GIS Cut Line= 5
     1826647.066      499996.009     1826692.205       500075.87
     1826784.219      500193.926     1826822.414      500291.148
     1826825.886      500374.481
#Sta/Elev= 26
       0  795.05    36.7  793.38    64.2  792.95    91.7  792.82   101.1  791.88
   110.4  788.69   119.8  783.33   129.2  782.44   138.5  782.53   149.8  782.85
   166.6  783.53   175.9  784.01   194.6   785.1   213.4  786.38   241.4   788.1
   260.4  788.82   279.4  789.22   288.9   789.3   298.4  789.26   307.9  789.14
   326.9  788.03   336.4  788.25   345.9  789.61   355.1  791.86   392.2  801.87
   429.3  811.72
#Mann= 3 , 0 , 0
       0      .1       0   129.2    .045       0   149.8      .1       0
Bank Sta=129.2,149.8
XS Rating Curve= 0 ,0
Exp/Cntr=0.3,0.1

Type RM Length L Ch R = 1 ,1925.7  ,189.9,194.3,198
XS GIS Cut Line= 4
     1826428.316      500027.259     1826612.344      500247.745
     1826659.219      500320.662     1826825.886      500416.148
#Sta/Elev= 30
       0  817.41    28.7  808.05    76.6  794.49    86.2   792.3    95.7  791.28
   143.6   789.7   181.9   787.6   229.8  785.61   239.3  785.43   248.9  785.58
   258.5  786.08     268  786.23   277.6  786.15   287.2  785.74   296.8  785.14
   306.5  783.77   316.1  781.74   325.7   780.5   336.5  781.33   354.6  785.09
   364.2  787.39   383.5  794.55   402.7  801.13   412.3  803.18   460.3  810.71
   479.5  813.35   489.1  814.09   517.9  817.08   546.8  819.36     566  821.34
#Mann= 3 , 0 , 0
       0      .1       0   316.1    .045       0   336.5      .1       0
Bank Sta=316.1,336.5
XS Rating Curve= 0 ,0
Exp/Cntr=0.3,0.1

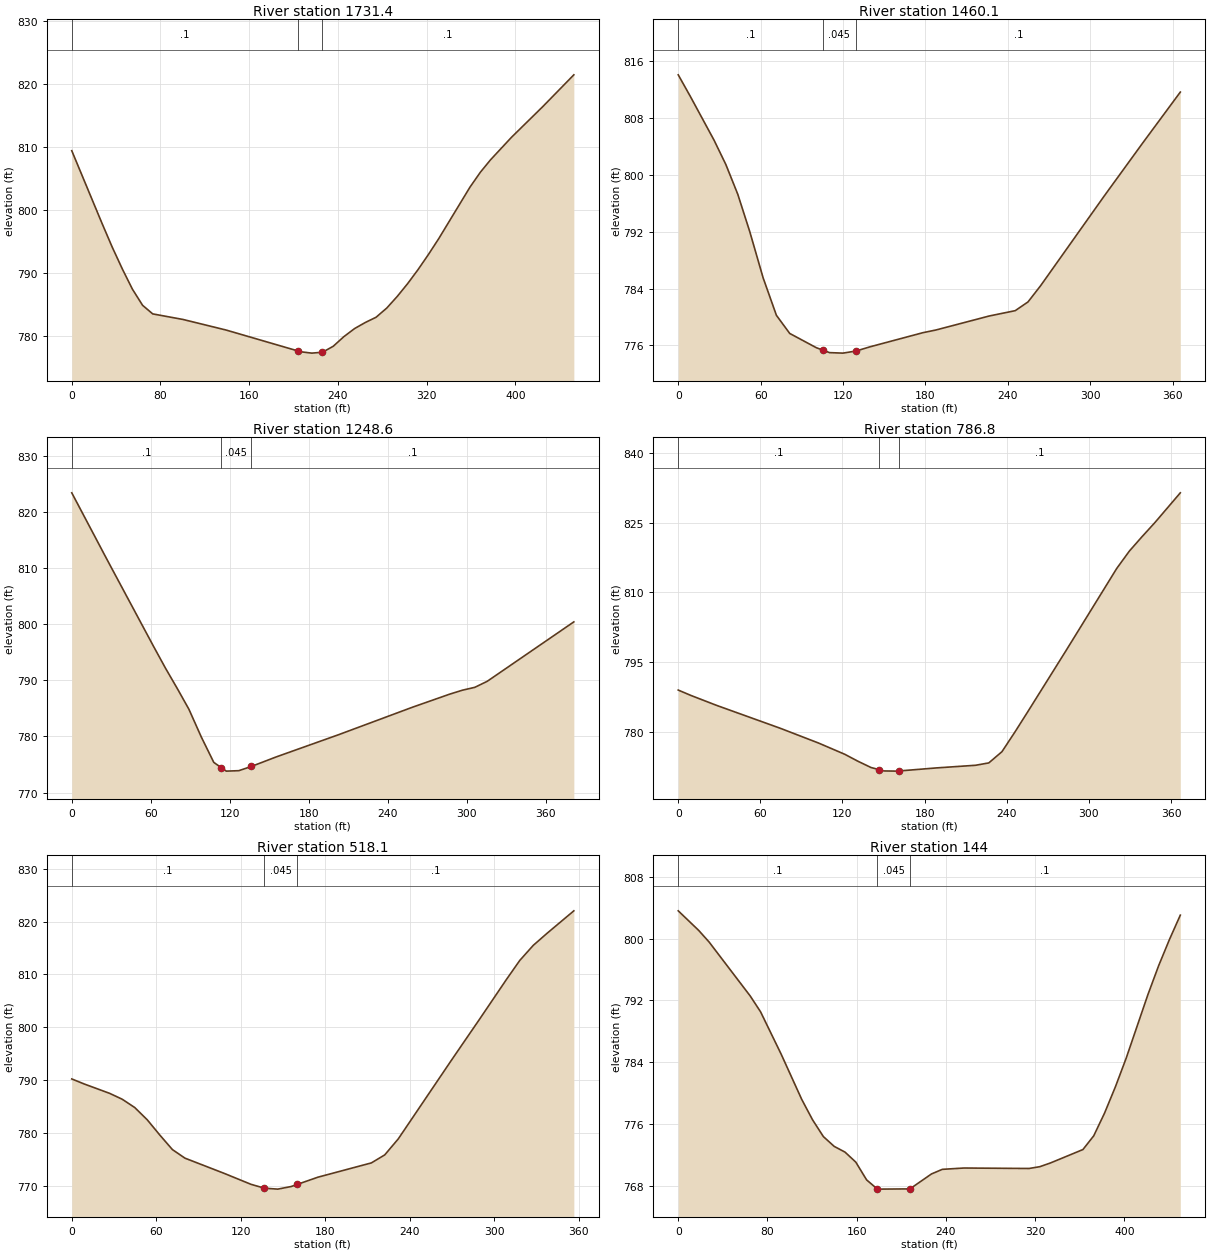
Type RM Length L Ch R = 1 ,1731.4  ,262.9,271.4,279.8
XS GIS Cut Line= 4
       1826355.4      500178.301     1826416.164      500258.162
     1826485.608      500428.301     1826475.191      500596.704
#Sta/Elev= 30
       0   809.4    27.4   797.8    36.5  794.06    45.6   790.6    54.7  787.38
    63.9  784.81      73  783.45   100.4  782.56     139  780.89   203.7  777.57
   206.7  777.42   216.4  777.21   226.1  777.35   235.8   778.3   245.4  779.83
   255.1  781.12   264.8  782.09   274.4  782.91   284.1  784.38   293.5  786.22
   302.9  788.26   312.2  790.47   321.6  792.88     331  795.43   359.1   803.6
   368.5  805.98   377.8  807.98   396.6  811.54   424.7   816.4   452.8  821.47
#Mann= 3 , 0 , 0
       0      .1       0   203.7    .045       0   226.1      .1       0
Bank Sta=203.7,226.1
XS Rating Curve= 0 ,0
Exp/Cntr=0.3,0.1

Type RM Length L Ch R = 1 ,1460.1  ,209.9,211.5,213
XS GIS Cut Line= 4
     1826188.733       500254.69     1826186.997      500306.773
     1826190.469      500490.801     1826216.511      500617.537
#Sta/Elev= 24
       0  814.11     8.7  811.11    26.1   804.9    34.7  801.47    43.4  797.27
    52.1  792.02    61.8  785.53    71.5  780.24    81.2  777.69   100.6  775.68
   105.1  775.36   110.2  774.99   119.9  774.92   129.6  775.22   139.3  775.79
     178  777.79   187.7  778.18   226.5  780.15   245.4   780.9   254.7  782.13
   263.9  784.42   310.1  797.02   337.8   804.4   365.6  811.68
#Mann= 3 , 0 , 0
       0      .1       0   105.1    .045       0   129.6      .1       0
Bank Sta=105.1,129.6
XS Rating Curve= 0 ,0
Exp/Cntr=0.3,0.1

Type RM Length L Ch R = 1 ,1248.6  ,449.9,461.8,473.5
XS GIS Cut Line= 4
     1825987.344      500235.592     1825978.664      500324.134
     1825973.455      500428.301      1825989.08      500615.801
#Sta/Elev= 20
       0   823.4    26.7  811.55    62.3  795.97    71.2  792.16    80.1  788.56
      89  784.84    98.4   779.9   107.9  775.37   113.7  774.42   117.4  773.82
   126.9   773.9   136.4  774.65   155.3  776.35   202.7  780.31   259.1  785.23
   287.3  787.55   296.8  788.24   306.2  788.75   315.6  789.82   381.4  800.41
#Mann= 3 , 0 , 0
       0      .1       0   113.7    .045       0   136.4      .1       0
Bank Sta=113.7,136.4
XS Rating Curve= 0 ,0
Exp/Cntr=0.3,0.1

Type RM Length L Ch R = 1 ,786.8   ,274.1,268.7,263.3
XS GIS Cut Line= 4
     1825655.096      500403.778     1825609.957      500495.792
     1825533.568       500617.32     1825495.374      500731.903
#Sta/Elev= 24
       0  789.01     9.3  787.85      28  785.72    74.5   780.8   102.5  777.62
   121.6  775.21   131.2  773.72   140.8  772.36   146.6  771.91   150.3  771.62
   159.9  771.58   161.6  771.62   188.6  772.27   217.3  772.84   226.9  773.35
   236.5  775.76     246     780   255.3  784.32   283.2  797.44   320.4  815.18
   329.6   818.9   338.9  822.01   348.2  825.01   366.8  831.42
#Mann= 3 , 0 , 0
       0      .1       0   146.6    .045       0   161.6      .1       0
Bank Sta=146.6,161.6
XS Rating Curve= 0 ,0
Exp/Cntr=0.3,0.1

Type RM Length L Ch R = 1 ,518.1   ,388.6,374.1,358.4
XS GIS Cut Line= 4
     1825369.289      500292.884     1825357.136      500381.426
     1825311.997      500506.426     1825279.011      500636.634
#Sta/Elev= 26
       0   790.2     8.9  789.24    26.8  787.48    35.8  786.36    44.7  784.79
    53.6  782.46    62.6  779.55    71.5  776.81    80.4  775.19   108.4  772.29
   127.3  770.23   136.8   769.5   146.3  769.32   155.8  769.81     160   770.2
   174.8  771.58   212.8  774.29   222.3  775.81   231.9  778.84   270.2  793.96
   289.4  801.43   308.6     809   318.2  812.66   327.8  815.52   337.4  817.76
   356.6  822.06
#Mann= 3 , 0 , 0
       0      .1       0   136.8    .045       0     160      .1       0
Bank Sta=136.8,160
XS Rating Curve= 0 ,0
Exp/Cntr=0.3,0.1

Type RM Length L Ch R = 1 ,144     ,142,144,146.9
XS GIS Cut Line= 3
     1824953.754      500143.548     1824977.939      500251.586
     1825080.653       500575.08
#Sta/Elev= 30
       0  803.59    18.4  801.05    27.7  799.55    64.6  792.56    73.8  790.53
    92.3  785.04   110.7   779.2   120.4  776.56   130.1  774.39   139.8  773.12
   149.5  772.38   159.2  771.08   168.9  768.78   178.6  767.59   207.7  767.62
   227.1  769.56   236.8  770.15   256.2  770.32   314.4  770.26   324.1  770.49
   333.8  770.98   362.8  772.71   372.5  774.49   382.2  777.43   391.9  780.82
   401.6  784.54     421  792.73   430.7   796.5   440.4  799.89   450.1  803.03
#Mann= 3 , 0 , 0
       0      .1       0   178.6    .045       0   207.7      .1       0
Bank Sta=178.6,207.7
XS Rating Curve= 0 ,0
Exp/Cntr=0.3,0.1

Chan Stop Cuts=-1
Use User Specified Reach Order=0
Composite Channel Slope=5